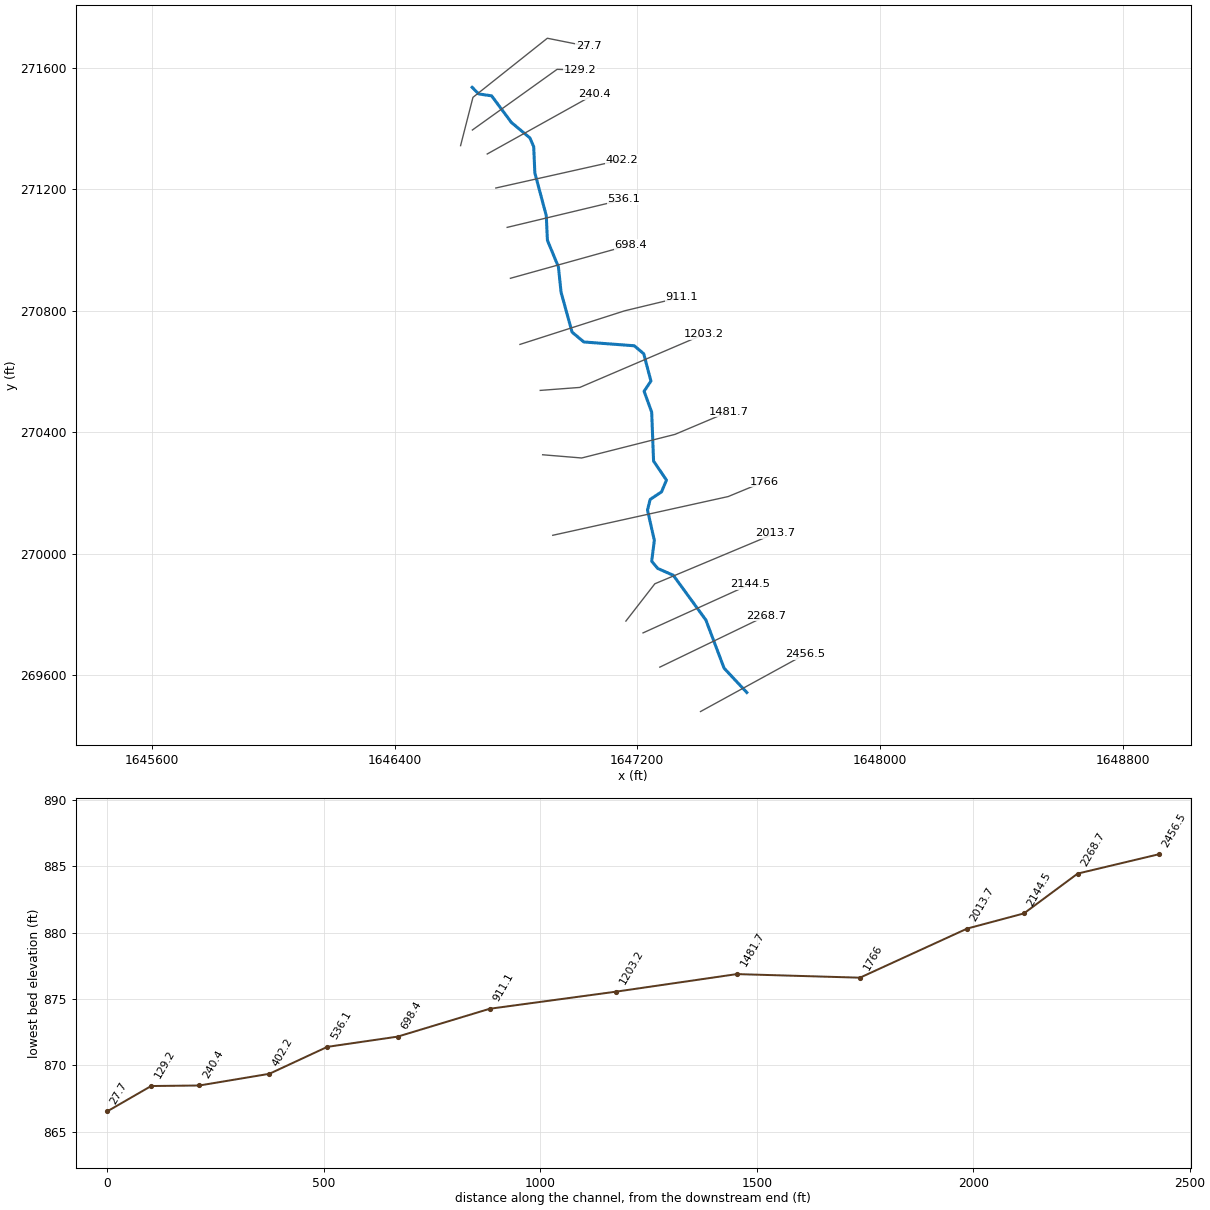
--- HUNTERFK.prj (project) ---

Proj Title=HUNTERFK
Current Plan=p01
Default Exp/Contr=0,0
English Units
Geom File=g01
Flow File=f01
Plan File=p01
BEGIN DESCRIPTION:
END DESCRIPTION:
DSS Export Rating Curves= 0
DSS Export Rating Curve Sorted= 0
DSS Export Volume Flow Curves= 0
DXF OffsetX= 0
DXF OffsetY= 0
DXF ScaleX= 0
DXF ScaleY= 0

--- HUNTERFK.p01 (plan) ---

Plan Title=Floodplain
Program Version=4.00
Geom File=g01
Flow File=f01
K Sum by GR=0
Std Step Tol=0.01
Critical Tol=0.01
Num of Std Step Trials=20
Max Error Tol=0.3
Flow Tol Ratio=0.001
Split Flow NTrial=30
Split Flow Tol=0.02
Split Flow Ratio=0.02
Log Output Level=0
Friction Slope Method=1
Unsteady Friction Slope Method=2
Unsteady Bridges Friction Slope Method=1
Global Log Level=0
CheckData=False
Run HTab=0
Run UNet=0
Run PostProcess=0
UNET Theta=0
UNET Theta Warmup=0
UNET ZTol=0
UNET ZSATol=0
UNET MxIter=0
UNET MaxInSteps=0
UNET DtIC=0
UNET DtMin=0
UNET MaxCRTS=0
UNET WFStab=0
UNET SFStab=0
UNET WFX=0
UNET SFX=0
UNET DSS MLevel=0
UNET DZMax Abort=0
UNET Convert EG Bridges=0
UNET Use Existing IB Tables=0
UNET Froude Limit=0
UNET Froude Power=0
Write IC File=0
Echo Input=False
Echo Output=False
Write Detailed=0

--- HUNTERFK.f01 (steady flow) ---

Flow Title=NFF Regression Equation
Program Version=4.10
Number of Profiles= 1
Profile Names=P100yr
River Rch & RM=HUNTERFK,Main            ,2456.5
757.8064
River Rch & RM=HUNTERFK,Main            ,536.1
841.3818
River Rch & RM=HUNTERFK,Main            ,240.4
844.9046
Boundary for River Rch & Prof#=HUNTERFK,Main            , 1
Up Type= 0
Dn Type= 3
Dn Slope=0.01831
DSS Import GetInterval= 0
DSS Import GetPeak= 0
DSS Import FillOption= 0

--- HUNTERFK.g01 (geometry) ---

Geom Title=USGS 10m DEM
Program Version=4.10

River Reach=HUNTERFK        ,Main
Reach XY= 30
     1647561.172      269542.322     1647486.201       269622.29
     1647426.225      269780.978     1647318.767       269928.42
     1647267.537      269950.911     1647247.545      269974.652
     1647256.292      270043.375       1647233.8      270143.335
     1647242.547      270178.321     1647280.032      270203.312
     1647296.276      270242.046     1647253.792      270304.772
     1647247.545      270465.958     1647222.555      270534.681
     1647245.046      270568.418     1647221.305      270658.383
     1647190.068      270684.622     1647023.883      270697.117
     1646985.148      270729.605     1646948.912      270860.803
     1646940.166       270944.52      1646903.93      271031.985
     1646900.181      271113.203     1646862.447      271254.398
     1646858.698      271340.614     1646846.203      271369.353
     1646784.977      271420.582     1646720.002      271508.048
     1646677.519      271514.296     1646655.783      271536.102

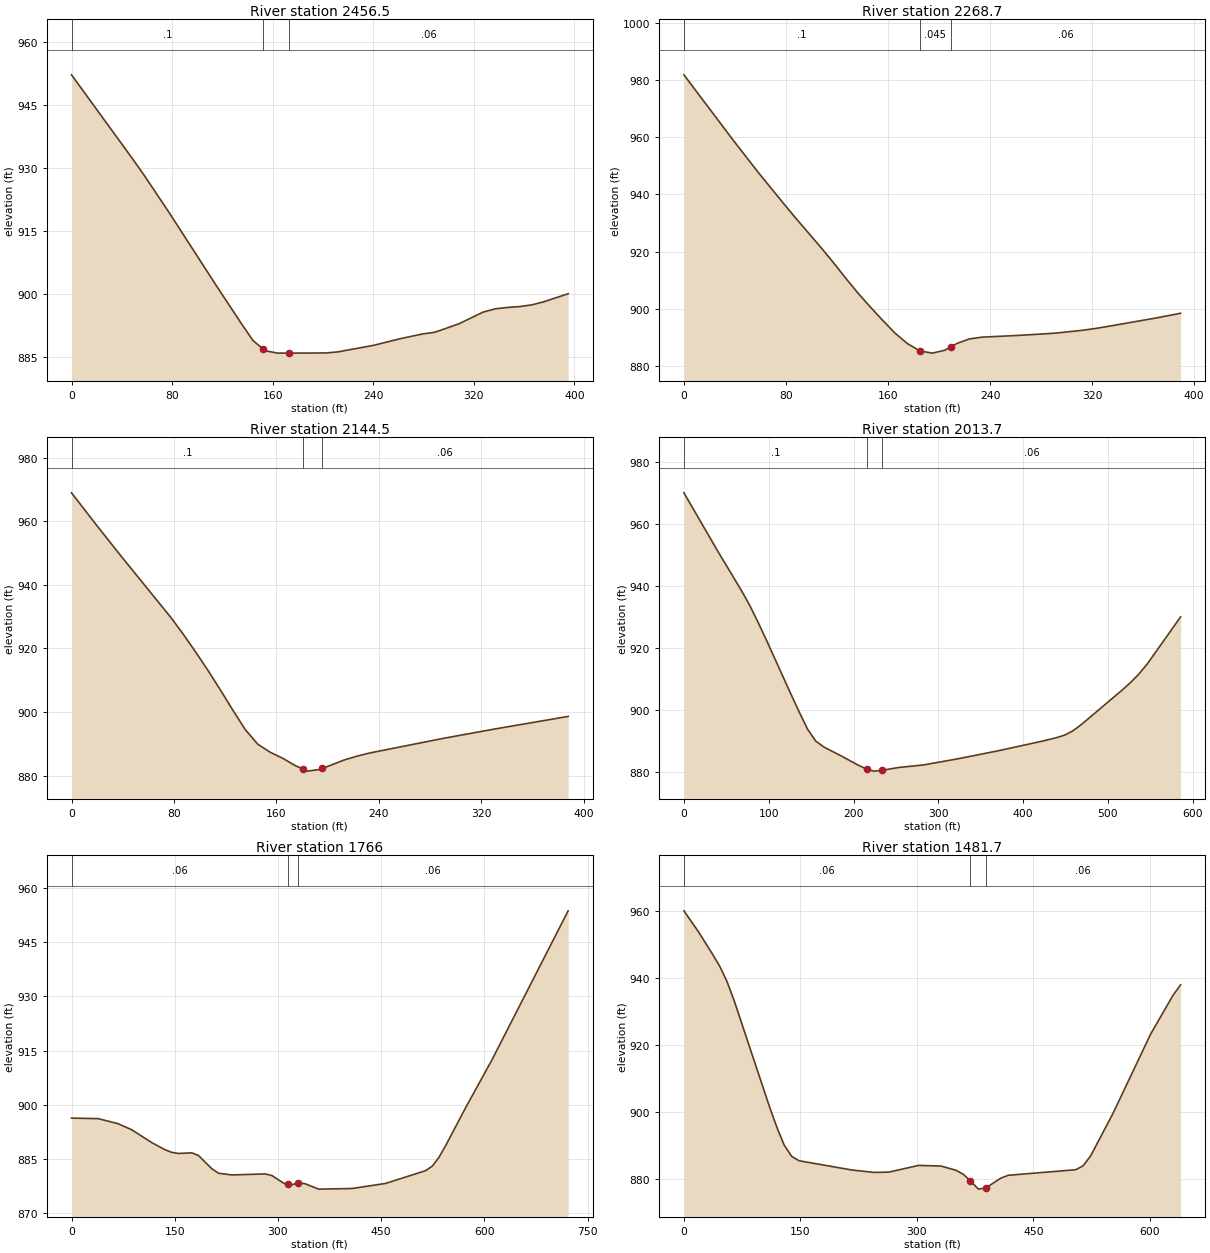
Type RM Length L Ch R = 1 ,2456.5  ,188.8,187.9,186.7
XS GIS Cut Line= 2
     1647408.457      269479.462     1647755.021      269669.143
#Sta/Elev= 26
       0   952.1    48.2  932.28    57.8  928.21    77.1  919.59   115.6  901.78
   134.9  893.04   144.5  888.85   152.4   886.9   154.2  886.46   163.8  885.91
   173.4   885.9   202.4  885.94     212   886.2   240.9  887.79   260.2  889.24
   269.8  889.86   279.4  890.46   289.1  890.87   308.4   892.9   327.6  895.68
   337.3  896.45   346.9  896.77   356.5  896.97   366.2  897.38   375.8  898.12
   395.1  900.03
#Mann= 3 , 0 , 0
       0      .1       0   152.4    .045       0   173.4     .06       0
Bank Sta=152.4,173.4
XS Rating Curve= 0 ,0
Exp/Cntr=0.3,0.1

Type RM Length L Ch R = 1 ,2268.7  ,124.7,124.1,123.4
XS GIS Cut Line= 2
     1647274.357      269625.774     1647625.052      269795.092
#Sta/Elev= 28
       0  981.87    38.9  958.82    58.4  947.64    77.9  936.95    87.6  931.74
   107.1   921.6   116.8  916.36   126.6  910.82   136.3  905.54     146  900.67
   155.8  895.93   165.5  891.45   175.2  887.79     185  885.21   194.7  884.44
   204.4  885.43   209.3  886.64   214.2  887.85   223.9  889.42   233.7  890.03
   262.9  890.66   282.3  891.18   292.1  891.48   311.5  892.39   321.3  892.98
     331  893.68     370  896.73   389.4  898.39
#Mann= 3 , 0 , 0
       0      .1       0     185    .045       0   209.3     .06       0
Bank Sta=185,209.3
XS Rating Curve= 0 ,0
Exp/Cntr=0.3,0.1

Type RM Length L Ch R = 1 ,2144.5  ,134.5,130.9,130.4
XS GIS Cut Line= 2
     1647219.047      269738.607     1647572.383      269898.932
#Sta/Elev= 24
       0  968.93    19.4  958.85    38.8     949    77.6  929.77    87.3  924.49
      97  918.89   106.7  913.05   116.4  906.91   126.1  900.58   135.8  894.48
   145.5  889.91   155.2  887.38   164.9   885.5   174.6  883.22     181  882.05
   184.3  881.44     194  881.97     196  882.28   213.4     885   223.1  886.15
   232.8  887.13     291  891.78   329.8  894.62     388  898.64
#Mann= 3 , 0 , 0
       0      .1       0     181    .045       0     196     .06       0
Bank Sta=181,196
XS Rating Curve= 0 ,0
Exp/Cntr=0.3,0.1

Type RM Length L Ch R = 1 ,2013.7  ,249,247.7,243.2
XS GIS Cut Line= 3
     1647162.569      269777.547     1647258.015      269900.475
     1647654.689      270066.616
#Sta/Elev= 30
       0     970    38.9  951.66    68.1  938.38    77.8  933.62    87.5  928.24
    97.3  922.53   126.4  904.99   136.2  899.23   145.9  893.78   155.6  889.94
   165.4  888.01     185  885.28   204.5  882.38   215.5  880.95     224   880.3
   233.8  880.57   253.4  881.48   282.7   882.3   321.8  884.21   370.7  886.86
   419.5  889.77   439.1  891.06   448.9   891.9   458.6  893.28   468.4  895.24
   517.3  906.54     527  908.94   536.8  911.67   546.6  914.91   585.7     930
#Mann= 3 , 0 , 0
       0      .1       0   215.5    .045       0   233.8     .06       0
Bank Sta=215.5,233.8
XS Rating Curve= 0 ,0
Exp/Cntr=0.3,0.1

Type RM Length L Ch R = 1 ,1766    ,282.5,284.3,285.6
XS GIS Cut Line= 3
     1646921.478      270060.192     1647499.603      270187.796
     1647619.394      270237.275
#Sta/Elev= 30
       0  896.27    38.8  896.13    67.9  894.71    87.4  893.06   116.5   889.5
   135.9  887.51   145.6  886.79   155.3  886.48   174.7  886.65   184.4  885.94
   203.8  882.26   213.5  881.01   232.9  880.53   281.5  880.81   291.2  880.36
   310.6  877.97   314.7   877.9   320.3   877.8   329.7   878.4   339.7  878.07
   359.1   876.6   407.6  876.77   456.2  878.17   514.4  881.71   524.1  882.96
   533.8  885.37   543.5  888.61   572.6  899.14   610.6   912.3   721.6  953.69
#Mann= 3 , 0 , 0
       0     .06       0   314.7    .045       0   329.7     .06       0
Bank Sta=314.7,329.7
XS Rating Curve= 0 ,0
Exp/Cntr=0.3,0.1

Type RM Length L Ch R = 1 ,1481.7  ,275.5,278.4,281.2
XS GIS Cut Line= 4
     1646888.146      270325.513      1647016.89      270314.878
     1647324.364      270392.682     1647502.207      270467.744
#Sta/Elev= 30
       0  959.99    18.4  953.84    36.9  947.03    46.1  943.43    55.4  938.91
    64.6  933.23   110.7  901.11     120  895.13   129.2  889.98   138.8  886.64
   148.4  885.34   215.7   882.6   244.5  881.86   263.7  881.95   302.2  883.96
     331  883.76   350.2  882.51   359.8  881.28   368.7  879.39   379.1  876.87
   388.7  877.22   407.9  880.14   417.5     881   504.3  882.66   513.9  883.83
   523.6  886.79   552.5  899.54   600.8  923.15   629.7  934.78   639.4  937.89
#Mann= 3 , 0 , 0
       0     .06       0   368.7    .045       0   388.7     .06       0
Bank Sta=368.7,388.7
XS Rating Curve= 0 ,0
Exp/Cntr=0.3,0.1

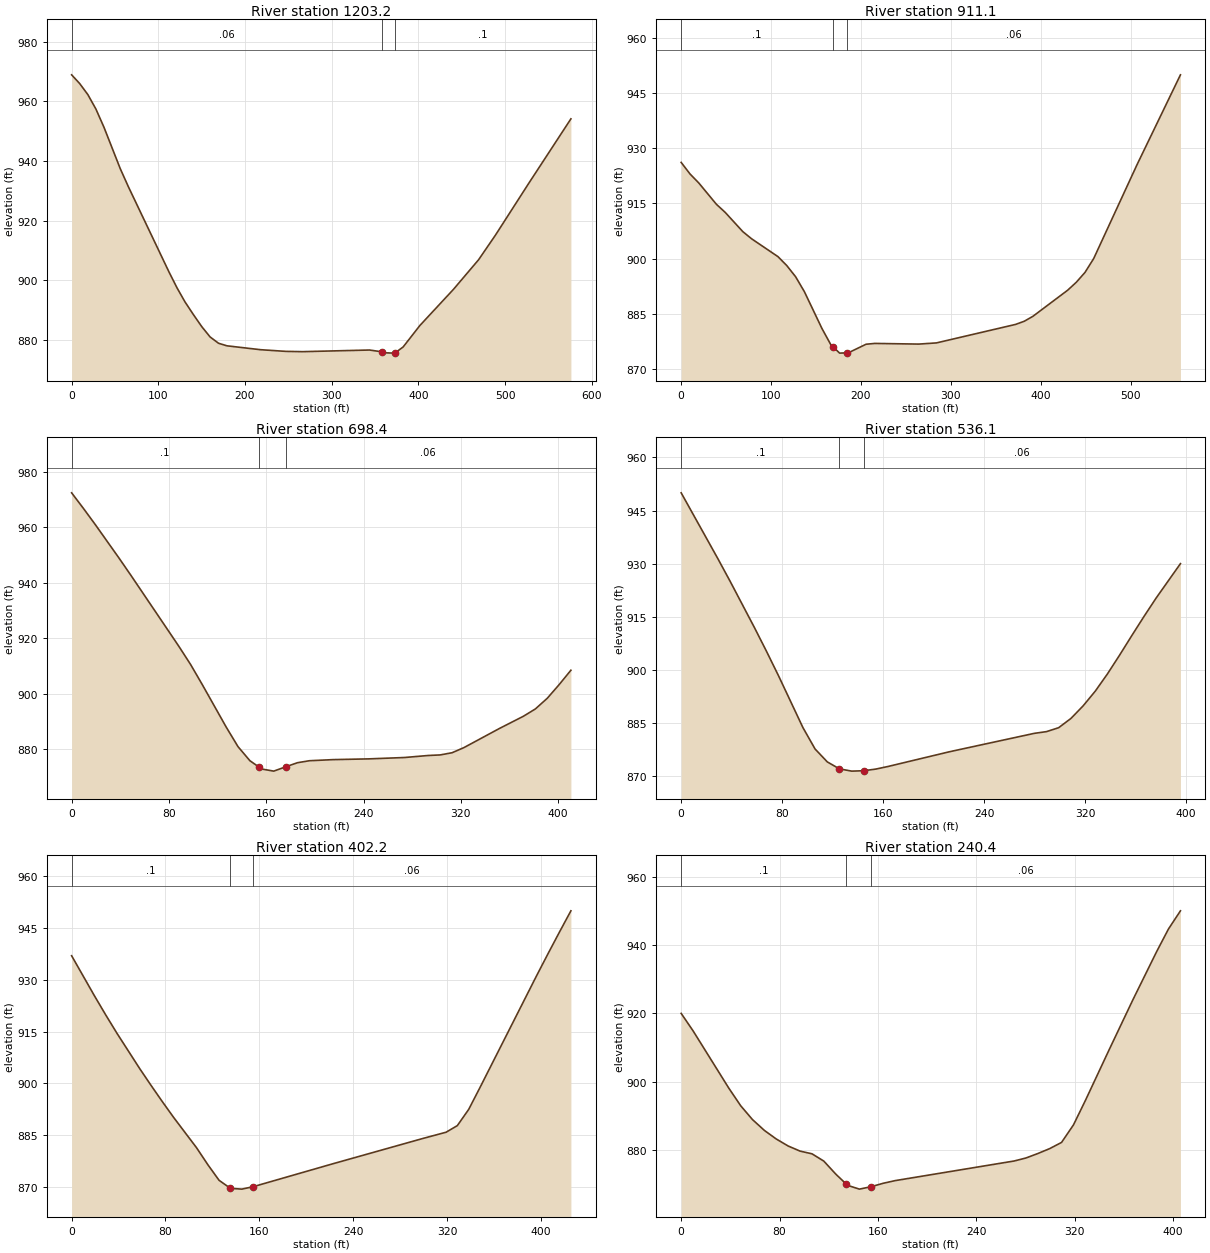
Type RM Length L Ch R = 1 ,1203.2  ,294.4,292.1,289.8
XS GIS Cut Line= 3
     1646880.255       270537.54     1647010.699      270547.383
     1647419.988      270722.455
#Sta/Elev= 30
       0  968.86     9.3  965.93    18.7  962.24      28   957.4    37.4  951.22
    56.1   937.4    65.4  931.38   112.1   902.9   121.5  897.48   130.8  892.72
   140.5  888.46   150.2  884.41   159.8  880.96   169.5  878.86   179.2     878
   217.9   876.7   246.9  876.14   266.3  876.04   343.7  876.59   358.6  875.96
   363.1  875.64   372.8  875.55   373.6  875.72   382.4   877.6   401.8  884.82
   440.5  896.93   469.5  906.86   488.9  915.09   527.6  932.59     576   954.1
#Mann= 3 , 0 , 0
       0     .06       0   358.6    .045       0   373.6      .1       0
Bank Sta=358.6,373.6
XS Rating Curve= 0 ,0
Exp/Cntr=0.3,0.1

Type RM Length L Ch R = 1 ,911.1   ,213.6,212.8,211.9
XS GIS Cut Line= 3
     1646813.405      270689.098     1647158.457      270799.775
     1647346.248      270844.996
#Sta/Elev= 30
       0  926.17     9.8  923.03    19.6  920.57    39.2  914.77      49  912.56
    68.6  907.32    78.4  905.37   107.7  900.52   117.5  898.09   127.3  895.06
   137.1  890.98   156.7  880.93   166.5  876.56     169  875.97   176.3  874.26
     184  874.34   186.1  874.36   205.7  876.68   215.5   876.9   264.4  876.72
     284  877.04     372  882.07   381.7  882.93   391.3  884.27     430  891.38
   439.6  893.54   449.3  896.23     459  900.01   507.2  925.55   555.5     950
#Mann= 3 , 0 , 0
       0      .1       0     169    .045       0     184     .06       0
Bank Sta=169,184
XS Rating Curve= 0 ,0
Exp/Cntr=0.3,0.1

Type RM Length L Ch R = 1 ,698.4   ,163,162.3,161.5
XS GIS Cut Line= 2
      1646781.97      270906.935     1647177.469      271017.004
#Sta/Elev= 30
       0  972.34     9.8  966.67    19.6  960.82    39.1  948.77    48.9  942.54
      88   917.2    97.8  910.56   107.5  903.25   127.1  888.01   136.8  880.97
   146.6   875.9   153.7  873.73   156.4  872.91   166.2  872.16   175.9   873.7
   185.7  875.19   195.5   875.9     215   876.3   244.4  876.57   273.7  877.06
   293.2  877.79     303  877.99   312.8  878.78   322.6  880.64   351.9  887.55
   371.4   891.9   381.2  894.52     391  898.35   400.8  903.28   410.5  908.48
#Mann= 3 , 0 , 0
       0      .1       0   153.7    .045       0   175.9     .06       0
Bank Sta=153.7,175.9
XS Rating Curve= 0 ,0
Exp/Cntr=0.3,0.1

Type RM Length L Ch R = 1 ,536.1   ,134.4,133.9,133.7
XS GIS Cut Line= 2
     1646771.298      271074.699     1647156.088      271166.641
#Sta/Elev= 27
       0     950      29  931.45    38.6  925.14    57.9  912.04    67.6  905.24
    77.2  898.28    96.5  883.67   106.1  877.64   115.8  873.99   125.4  872.03
   135.1  871.39   144.7   871.5   154.4  871.98     164  872.71   212.3  876.84
   279.8  882.06   289.5  882.55   299.1  883.66   308.8  886.26   318.4  889.79
   328.1  893.98   337.7  898.82   347.4  904.16     357  909.64   366.7  915.07
   376.3  920.26   395.6     930
#Mann= 3 , 0 , 0
       0      .1       0   125.4    .045       0   144.7     .06       0
Bank Sta=125.4,144.7
XS Rating Curve= 0 ,0
Exp/Cntr=0.3,0.1

Type RM Length L Ch R = 1 ,402.2   ,155.7,161.7,168.4
XS GIS Cut Line= 2
     1646733.844      271204.373      1647149.13      271297.279
#Sta/Elev= 24
       0     937    19.3  925.48      29  919.89    38.7   914.5      58  904.31
    67.7  899.43    77.4  894.68      87  890.12   106.4   881.4   116.1  876.45
   125.7  871.91   135.4  869.59   145.1  869.36   154.8  870.07   222.4  876.68
   299.8  884.08   319.2  885.85   328.8  887.77   338.5  892.48   348.2  898.88
   396.5  931.31   406.2  937.66   415.9   943.9   425.6  950.02
#Mann= 3 , 0 , 0
       0      .1       0   135.4    .045       0   154.8     .06       0
Bank Sta=135.4,154.8
XS Rating Curve= 0 ,0
Exp/Cntr=0.3,0.1

Type RM Length L Ch R = 1 ,240.4   ,107.7,111.2,113.6
XS GIS Cut Line= 2
     1646705.546      271316.486     1647060.451      271513.912
#Sta/Elev= 30
       0  919.98     9.7  914.85    38.7   898.1    48.4  892.92      58  888.86
    67.7  885.68    77.4  883.16      87  881.12    96.7  879.62   106.4  878.83
     116   876.7   125.7   872.9   134.1  870.02   135.4  869.58     145  868.48
   154.7  869.21   164.4   870.2     174  870.97   270.8  876.72   280.4   877.6
   290.1  878.91   299.8  880.36   309.4  882.17   319.1  887.31   328.8  894.47
   348.1  909.32   367.4  923.95   386.8  938.12   396.4  944.73   406.1  950.03
#Mann= 3 , 0 , 0
       0      .1       0   134.1    .045       0   154.7     .06       0
Bank Sta=134.1,154.7
XS Rating Curve= 0 ,0
Exp/Cntr=0.3,0.1

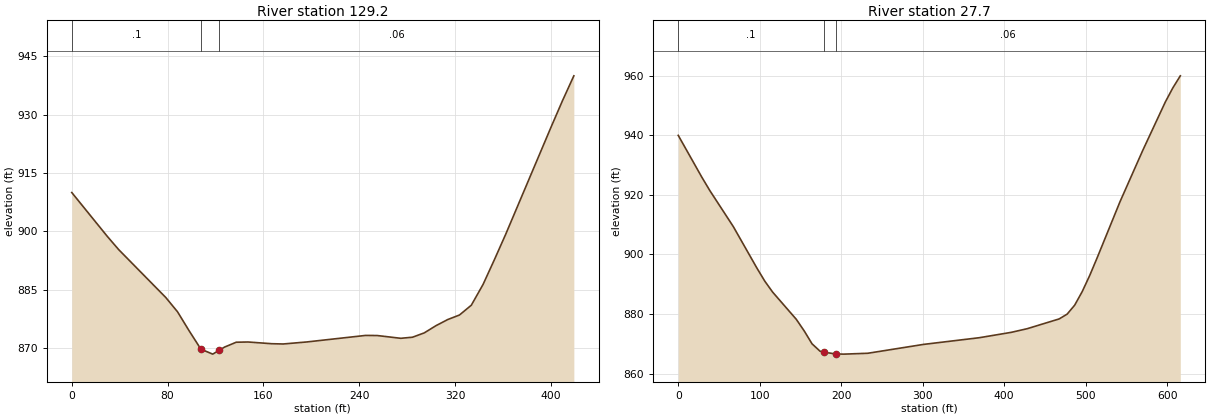
Type RM Length L Ch R = 1 ,129.2   ,97.8,101.5,103.4
XS GIS Cut Line= 3
     1646656.601      271395.492     1646935.801      271595.348
     1647011.571      271592.983
#Sta/Elev= 30
       0     910    29.4  898.82    39.2  895.31    78.5     883    88.3  879.33
    98.1  874.39   107.8  869.72   117.7  868.44   122.8  869.38   127.5  870.24
   137.3   871.5   147.2  871.56   166.8  871.12   176.6  871.05   196.2  871.57
   245.3  873.25   255.1  873.22   274.7  872.51   284.5  872.79   294.3   873.9
   304.1  875.76   313.9  877.33   323.7   878.5   333.6  881.02   343.4  886.36
   352.8  892.68   362.3  899.26   400.2  926.84   409.7   933.6   419.2  940.01
#Mann= 3 , 0 , 0
       0      .1       0   107.8    .045       0   122.8     .06       0
Bank Sta=107.8,122.8
XS Rating Curve= 0 ,0
Exp/Cntr=0.3,0.1

Type RM Length L Ch R = 1 ,27.7    ,26,27.7,30.8
XS GIS Cut Line= 4
     1646617.723      271343.958     1646658.482      271503.036
      1646903.65      271697.787     1647039.844      271670.665
#Sta/Elev= 30
       0     940      29  925.94    38.6  921.54    67.6  909.36    96.6  895.41
   106.3  891.01   115.9  887.35   144.9  878.22   154.6  874.33   164.2     870
     174  867.52   178.3  867.21   193.3  866.58   203.4  866.53   232.7  866.82
   301.2   869.8   369.7  872.05   408.8  873.85   428.4  875.08   467.5  878.35
   477.3  879.96   486.6  882.99   495.8  887.53   505.1     893   514.4  899.05
   542.1  917.66   569.9  934.83   597.7  951.15   606.9  955.89   616.2     960
#Mann= 3 , 0 , 0
       0      .1       0   178.3    .045       0   193.3     .06       0
Bank Sta=178.3,193.3
XS Rating Curve= 0 ,0
Exp/Cntr=0.3,0.1

Chan Stop Cuts=-1
Use User Specified Reach Order=0
Composite Channel Slope=5